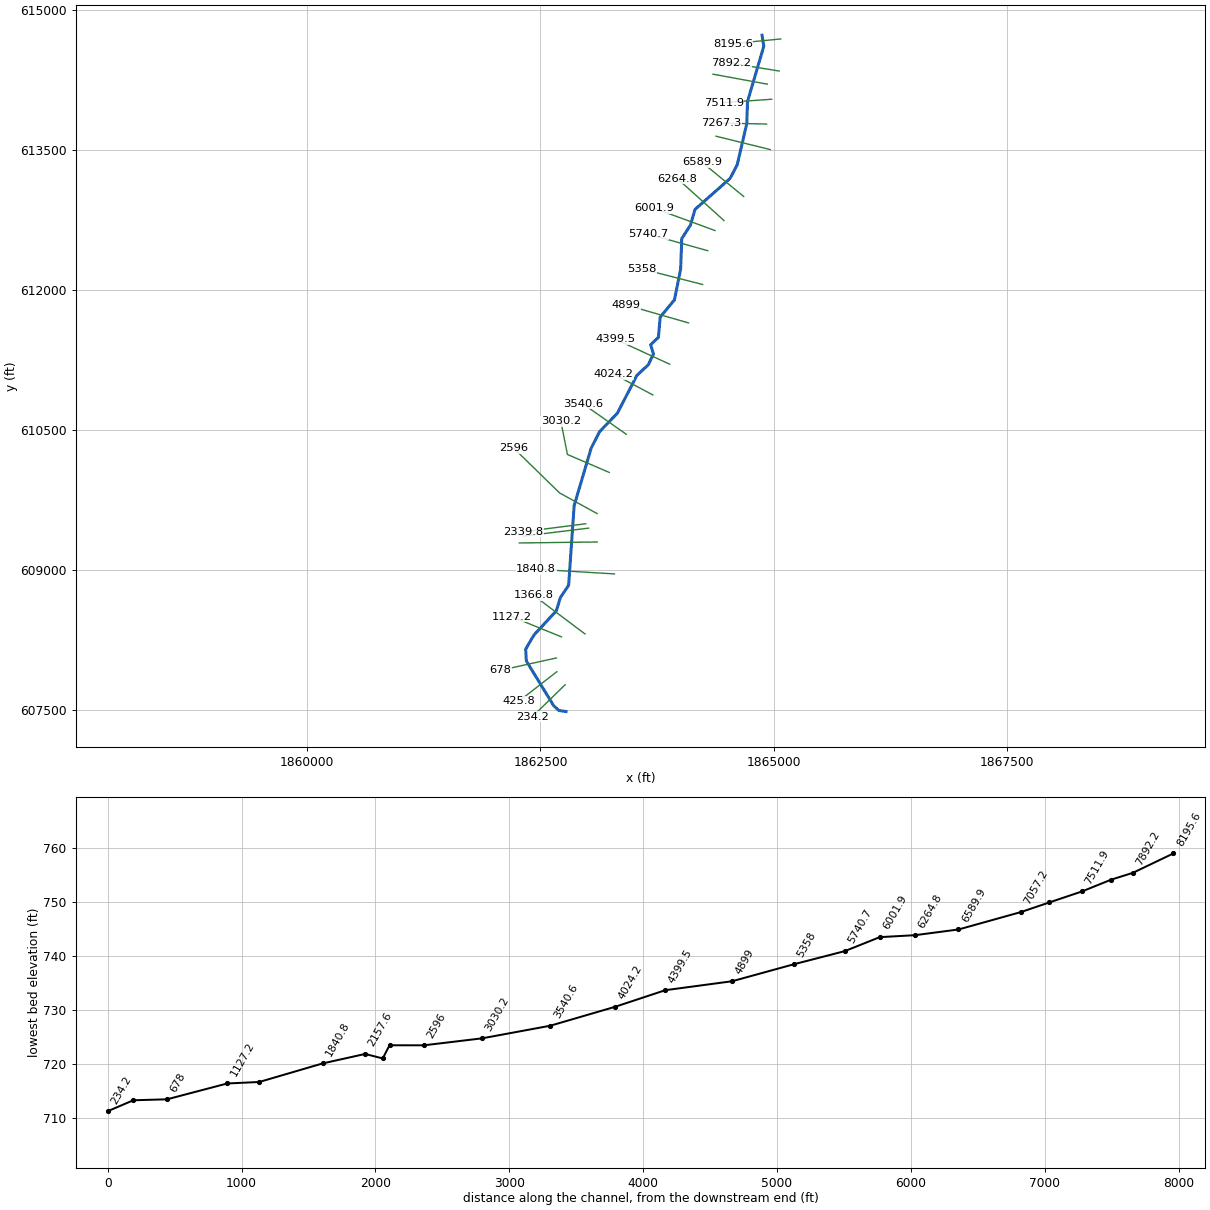
--- RndKnobRun.prj (project) ---

Proj Title=RndKnobRun
Current Plan=p01
Default Exp/Contr=0,0
English Units
Geom File=g01
Flow File=f01
Plan File=p01
BEGIN DESCRIPTION:
AMEC Environment & Infrastructure, 2013
Projection: NAD 1983 State Plane West Virginia South FIPS 4702 (US Feet)
Vertical Datum: NAVD 1988
END DESCRIPTION:
DSS Export Rating Curves= 0
DSS Export Rating Curve Sorted= 0
DSS Export Volume Flow Curves= 0
DXF OffsetX= 0
DXF OffsetY= 0
DXF ScaleX= 0
DXF ScaleY= 0

--- RndKnobRun.p01 (plan) ---

Plan Title=Floodplain
Program Version=4.00
Geom File=g01
Flow File=f01
K Sum by GR=0
Std Step Tol=0.01
Critical Tol=0.01
Num of Std Step Trials=20
Max Error Tol=0.3
Flow Tol Ratio=0.001
Split Flow NTrial=30
Split Flow Tol=0.02
Split Flow Ratio=0.02
Log Output Level=0
Friction Slope Method=1
Unsteady Friction Slope Method=2
Unsteady Bridges Friction Slope Method=1
Global Log Level=0
CheckData=False
Run HTab=0
Run UNet=0
Run PostProcess=0
UNET Theta=0
UNET Theta Warmup=0
UNET ZTol=0
UNET ZSATol=0
UNET MxIter=0
UNET MaxInSteps=0
UNET DtIC=0
UNET DtMin=0
UNET MaxCRTS=0
UNET WFStab=0
UNET SFStab=0
UNET WFX=0
UNET SFX=0
UNET DSS MLevel=0
UNET DZMax Abort=0
UNET Convert EG Bridges=0
UNET Use Existing IB Tables=0
UNET Froude Limit=0
UNET Froude Power=0
Write IC File=0
Echo Input=False
Echo Output=False
Write Detailed=0

--- RndKnobRun.f01 (steady flow) ---

Flow Title=NFF Regression Equation
Program Version=4.00
Number of Profiles=1
Profile Names=P100yr
River Rch & RM=RndKnobRun,Main      ,8195.6
1079.751
River Rch & RM=RndKnobRun,Main      ,2596
1196.674
River Rch & RM=RndKnobRun,Main      ,425.8
1280.842
River Rch & RM=RndKnobRun,Main      ,234.2
1283.350
Boundary for River Rch & Prof#=RndKnobRun,Main      ,1
Up Type=0
Dn Type=3
Dn Slope=0.006335

--- RndKnobRun.g01 (geometry) ---

Geom Title=USGS 3m DEM
Program Version=4.10

River Reach=RndKnobRun      ,Main
Reach XY= 30
     1864872.856      614728.589     1864891.889      614610.033
     1864717.462      614018.618     1864709.569      613781.608
     1864607.121      613340.477     1864530.099      613193.976
     1864155.595      612862.859     1864105.237      612692.658
     1864013.197      612550.243     1864001.055      612222.002
     1863935.074       611893.76      1863782.25      611709.661
     1863763.156       611492.57     1863679.797      611412.677
       1863709.9      611314.173     1863655.492      611199.059
      1863532.19      611084.431     1863323.801      610679.766
      1863132.77      610481.772     1863042.469      610304.623
     1862860.611      609689.946     1862801.512      608836.868
     1862713.032      608705.221      1862669.62      608562.808
     1862429.965      608304.027     1862341.399      608152.929
     1862348.351      608026.149      1862640.14      607548.564
     1862696.518      607495.824     1862773.814       607484.51

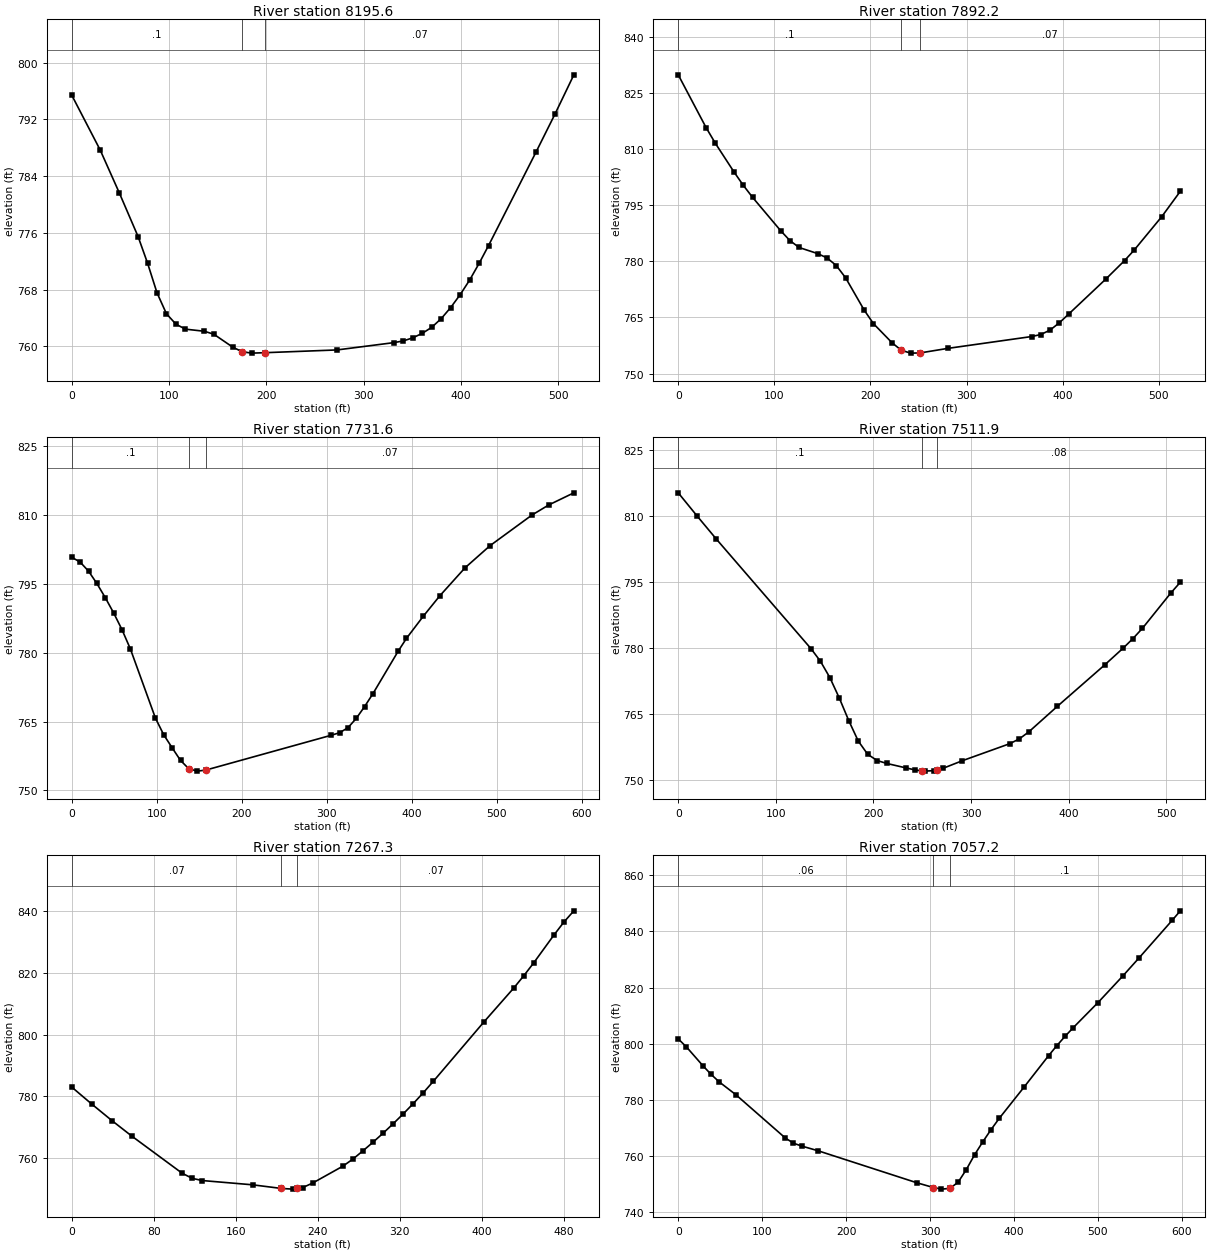
Type RM Length L Ch R = 1 ,8195.6  ,309.3,303.4,297.6
XS GIS Cut Line= 2
     1865073.656      614688.324     1864560.273      614637.992
#Sta/Elev= 30
       0  795.41    29.2  787.68    48.7  781.68    68.1  775.49    77.9  771.72
    87.6  767.54    97.3  764.59   107.1  763.12   116.8  762.43   136.3  762.13
     146  761.71   165.5  759.88   175.2  759.24   184.9  759.05   198.3  759.11
   272.5   759.5   330.9  760.53   340.6  760.77   350.4  761.21   360.1  761.84
   369.8  762.69   379.6  763.92   389.3  765.48     399  767.29   408.8  769.36
   418.5  771.71   428.2  774.22   476.9  787.38   496.4  792.74   515.8  798.28
#Mann= 3 , 0 , 0
       0      .1       0   175.2    .045       0   198.3     .07       0
Bank Sta=175.2,198.3
XS Rating Curve= 0 ,0
Exp/Cntr=0.3,0.1

Type RM Length L Ch R = 1 ,7892.2  ,161.1,160.6,159.9
XS GIS Cut Line= 2
     1865056.939      614344.751     1864541.314      614428.084
#Sta/Elev= 30
       0  829.81      29   815.7    38.7  811.48      58  803.86    67.7  800.28
    77.4  797.05   106.4  788.21   116.1  785.54   125.7  783.68   145.1  782.04
   154.8  780.88   164.4  778.86   174.1  775.58   193.4  766.96   203.1  763.32
   222.5   758.2   232.1  756.21   241.8  755.45   251.5   755.5   280.5  756.72
   367.6  759.88   377.2  760.42   386.9  761.62   396.6  763.59   406.2  765.89
   444.9  775.26   464.3  780.18     474  782.89     503  791.92   522.3  798.69
#Mann= 3 , 0 , 0
       0      .1       0   232.1    .045       0   251.5     .07       0
Bank Sta=232.1,251.5
XS Rating Curve= 0 ,0
Exp/Cntr=0.3,0.1

Type RM Length L Ch R = 1 ,7731.6  ,213.3,219.8,225.9
XS GIS Cut Line= 2
     1864929.335      614204.126     1864348.606      614310.897
#Sta/Elev= 30
       0  800.78     9.8  799.74    19.7  797.77    29.5  795.08    39.4  791.99
    49.2  788.68      59  785.04    68.9  780.83    98.4  765.75   108.2   762.1
   118.1  759.27   127.9  756.53   137.8  754.69   147.6   754.2   157.5  754.42
   305.1  762.01   314.9  762.56   324.8  763.65   334.6  765.69   344.4  768.26
   354.3   771.1   383.8   780.3   393.6  783.11   413.3  787.91     433  792.42
   462.5  798.48     492  803.32   541.3  809.99   560.9  812.17   590.5  814.82
#Mann= 3 , 0 , 0
       0      .1       0   137.8    .045       0   157.5     .07       0
Bank Sta=137.8,157.5
XS Rating Curve= 0 ,0
Exp/Cntr=0.3,0.1

Type RM Length L Ch R = 1 ,7511.9  ,247.1,244.5,241.9
XS GIS Cut Line= 2
      1864976.21      614042.667     1864463.189      614006.209
#Sta/Elev= 30
       0  815.17    19.4  809.89    38.8  804.73   135.9  779.82   145.6  776.96
   155.3  773.24     165  768.58   174.7  763.45   184.4  758.83   194.1  755.81
   203.8   754.4   213.5  753.75   232.9  752.75   242.6  752.27   249.7  752.07
   252.3     752     262  752.11   264.7  752.27   271.7  752.68   291.1  754.37
   339.6  758.23   349.4  759.32     359  760.89   388.2  766.68   436.7  776.08
   456.1  779.99   465.8  782.09   475.5  784.42   504.6  792.44   514.3  794.87
#Mann= 3 , 0 , 0
       0      .1       0   249.7    .045       0   264.7     .08       0
Bank Sta=249.7,264.7
XS Rating Curve= 0 ,0
Exp/Cntr=0.3,0.1

Type RM Length L Ch R = 1 ,7267.3  ,215.1,210.1,205.1
XS GIS Cut Line= 2
     1864921.522      613777.042     1864431.939      613787.459
#Sta/Elev= 30
       0     783    19.6  777.48    39.2  772.15    58.8  767.07   107.7   755.1
   117.5  753.45   127.3  752.74   176.3  751.36   204.5  750.18   215.5  749.96
   219.5  750.17   225.3  750.47     235  751.94   264.4  757.39   274.2  759.69
     284  762.36   293.8  765.15   303.6  768.06   313.4  771.11   323.2   774.3
     333  777.64   342.8  781.16   352.6  784.86   401.6  803.96   430.9  815.02
   440.7     819   450.5  823.22   470.1  832.18   479.9  836.42   489.7   840.1
#Mann= 3 , 0 , 0
       0     .07       0   204.5    .045       0   219.5     .07       0
Bank Sta=204.5,219.5
XS Rating Curve= 0 ,0
Exp/Cntr=0.3,0.1

Type RM Length L Ch R = 1 ,7057.2  ,477.3,467.3,457.3
XS GIS Cut Line= 2
     1864960.585      613503.605     1864379.856      613646.834
#Sta/Elev= 30
       0   801.7     9.8  798.82    29.4  792.14    39.2  789.04      49  786.33
    68.6  781.83   127.5  766.41   137.3  764.54   147.1  763.53   166.7  761.84
   284.4  750.44     304  748.76   313.6  748.19   323.6  748.45   333.4  750.64
   343.2  755.17     353  760.41   362.8  765.04   372.6  769.37   382.4   773.4
   411.8  784.47   441.2  795.72     451  799.29   460.9  802.65   470.7  805.74
   500.1  814.65   529.5  824.07   549.1  830.59   588.3  843.89   598.1  847.31
#Mann= 3 , 0 , 0
       0     .06       0     304    .045       0   323.6      .1       0
Bank Sta=304,323.6
XS Rating Curve= 0 ,0
Exp/Cntr=0.3,0.1

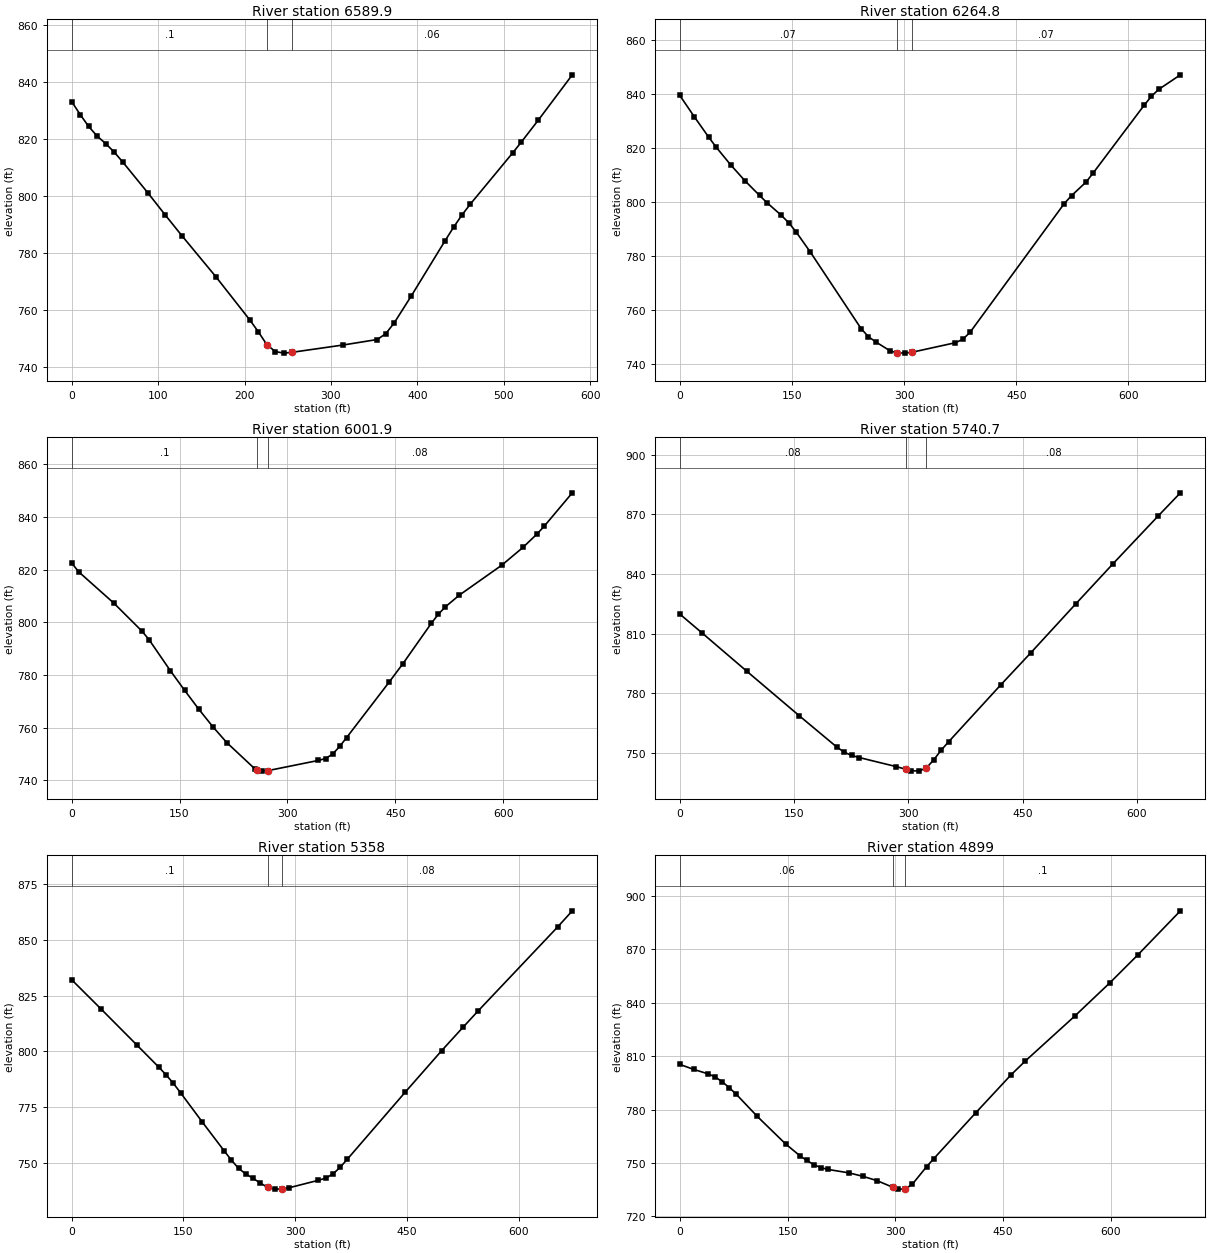
Type RM Length L Ch R = 1 ,6589.9  ,325.5,325.1,323.6
XS GIS Cut Line= 2
     1864676.731      613001.001     1864228.814      613368.188
#Sta/Elev= 30
       0  833.17     9.8  828.62    19.6  824.46    29.4  821.07    39.3  818.45
    49.1  815.48    58.9  812.04    88.4  801.06     108  793.49   127.6   786.1
   166.9  771.72   206.2  756.55     216  752.42   225.8  747.92   235.6  745.51
   245.4  744.96   255.2  745.26   314.1  747.81   353.4  749.73   363.2  751.72
     373  755.49   392.7   764.9   431.9  784.32   441.8  789.08   451.6  793.42
   461.4  797.28   510.5  815.27   520.3     819   539.9  826.67   579.2  842.55
#Mann= 3 , 0 , 0
       0      .1       0   225.8    .045       0   255.2     .06       0
Bank Sta=225.8,255.2
XS Rating Curve= 0 ,0
Exp/Cntr=0.3,0.1

Type RM Length L Ch R = 1 ,6264.8  ,254.3,263,271.7
XS GIS Cut Line= 2
     1864465.793      612743.188     1863968.397      613191.105
#Sta/Elev= 30
       0  839.31    19.4  831.41    38.8  823.79    48.5   820.2    67.9  813.64
    87.3  807.66   106.7  802.26   116.4  799.64   135.8   794.9   145.5  792.21
   155.2   788.9   174.6   781.3   242.5  752.95   252.2     750   261.9  748.08
   281.3  744.73   290.2  744.02   300.7   743.9   310.4  744.22   368.6  747.76
   378.3  749.01     388  751.55   514.1  799.26   523.8   802.2   543.2  807.21
   552.9  810.63   620.8  835.62   630.6  838.96   640.2   841.5   669.4  846.93
#Mann= 3 , 0 , 0
       0     .07       0   290.2    .045       0   310.4     .07       0
Bank Sta=290.2,310.4
XS Rating Curve= 0 ,0
Exp/Cntr=0.3,0.1

Type RM Length L Ch R = 1 ,6001.9  ,259.4,261.2,262.8
XS GIS Cut Line= 2
     1864369.439      612636.417     1863715.793      612876.001
#Sta/Elev= 30
       0  822.48     9.8  819.13    58.8  807.22      98  796.57   107.9  793.28
   137.3   781.6   156.9  774.24   176.5  767.12   196.1  760.45   215.7  754.36
   254.9  744.36   258.2  744.08   264.7  743.54   273.2  743.75   343.2   747.6
     353  748.31   362.8  749.97   372.6  752.89   382.4  756.28   441.2   777.2
   460.8  784.36   500.1   799.6   509.9  803.05   519.7  805.86   539.3  810.34
   598.1  821.65   627.5  828.38   647.1  833.48     657  836.39   696.2  849.11
#Mann= 3 , 0 , 0
       0      .1       0   258.2    .045       0   273.2     .08       0
Bank Sta=258.2,273.2
XS Rating Curve= 0 ,0
Exp/Cntr=0.3,0.1

Type RM Length L Ch R = 1 ,5740.7  ,381.7,382.7,382.8
XS GIS Cut Line= 2
     1864291.314      612420.272     1863658.501      612597.355
#Sta/Elev= 22
       0   819.9    29.4  810.35    88.3  791.05   156.9  768.76     206  753.08
   215.8  750.47   225.6  748.82   235.4  747.79   284.4  743.19   296.3  741.94
     304   741.2   313.8  740.95   323.7  742.52   333.5  746.72   343.3  751.59
   353.1   755.8   421.7  784.47     461  800.53   519.8  825.03   568.8  845.25
   627.7   869.1   657.1  880.84
#Mann= 3 , 0 , 0
       0     .08       0   296.3    .045       0   323.7     .08       0
Bank Sta=296.3,323.7
XS Rating Curve= 0 ,0
Exp/Cntr=0.3,0.1

Type RM Length L Ch R = 1 ,5358    ,458.3,459,457.5
XS GIS Cut Line= 2
     1864236.626      612058.292     1863585.585      612224.959
#Sta/Elev= 29
       0  832.03      39  819.11    87.7  802.81   116.9     793   126.6  789.59
   136.4   785.8   146.1  781.57   175.3  768.49   204.5  755.68   214.3  751.48
     224  747.79   233.8  745.25   243.5  743.32   253.2  741.19     263  739.31
   272.7   738.5   282.4  738.55   292.2  739.14   331.2  742.45   340.9   743.4
   350.6  745.24   360.4  748.26   370.1   751.9     448  781.92   496.7  800.38
   525.9  811.02   545.4  818.04   652.6  855.71     672  862.83
#Mann= 3 , 0 , 0
       0      .1       0     263    .045       0   282.4     .08       0
Bank Sta=263,282.4
XS Rating Curve= 0 ,0
Exp/Cntr=0.3,0.1

Type RM Length L Ch R = 1 ,4899    ,502.4,499.5,495.7
XS GIS Cut Line= 2
     1864085.585      611646.834     1863416.314      611839.542
#Sta/Elev= 30
       0  805.43    19.6  802.58    39.2  800.14      49  798.43    58.9   795.7
    68.7  792.39    78.5  788.68   107.9  776.18   147.1   760.8   166.8  754.21
   176.6   751.5   186.4  749.16   196.2  747.46     206  746.44   235.4   744.5
     255  742.54   274.7   740.1   296.5  736.39   304.1  735.37   313.9  735.42
   323.7  738.21   343.3  747.92   353.1  752.36     412  778.35     461  799.62
   480.7  807.32   549.3  832.48   598.4  851.26   637.6  867.06   696.5  891.69
#Mann= 3 , 0 , 0
       0     .06       0   296.5    .045       0   313.9      .1       0
Bank Sta=296.5,313.9
XS Rating Curve= 0 ,0
Exp/Cntr=0.3,0.1

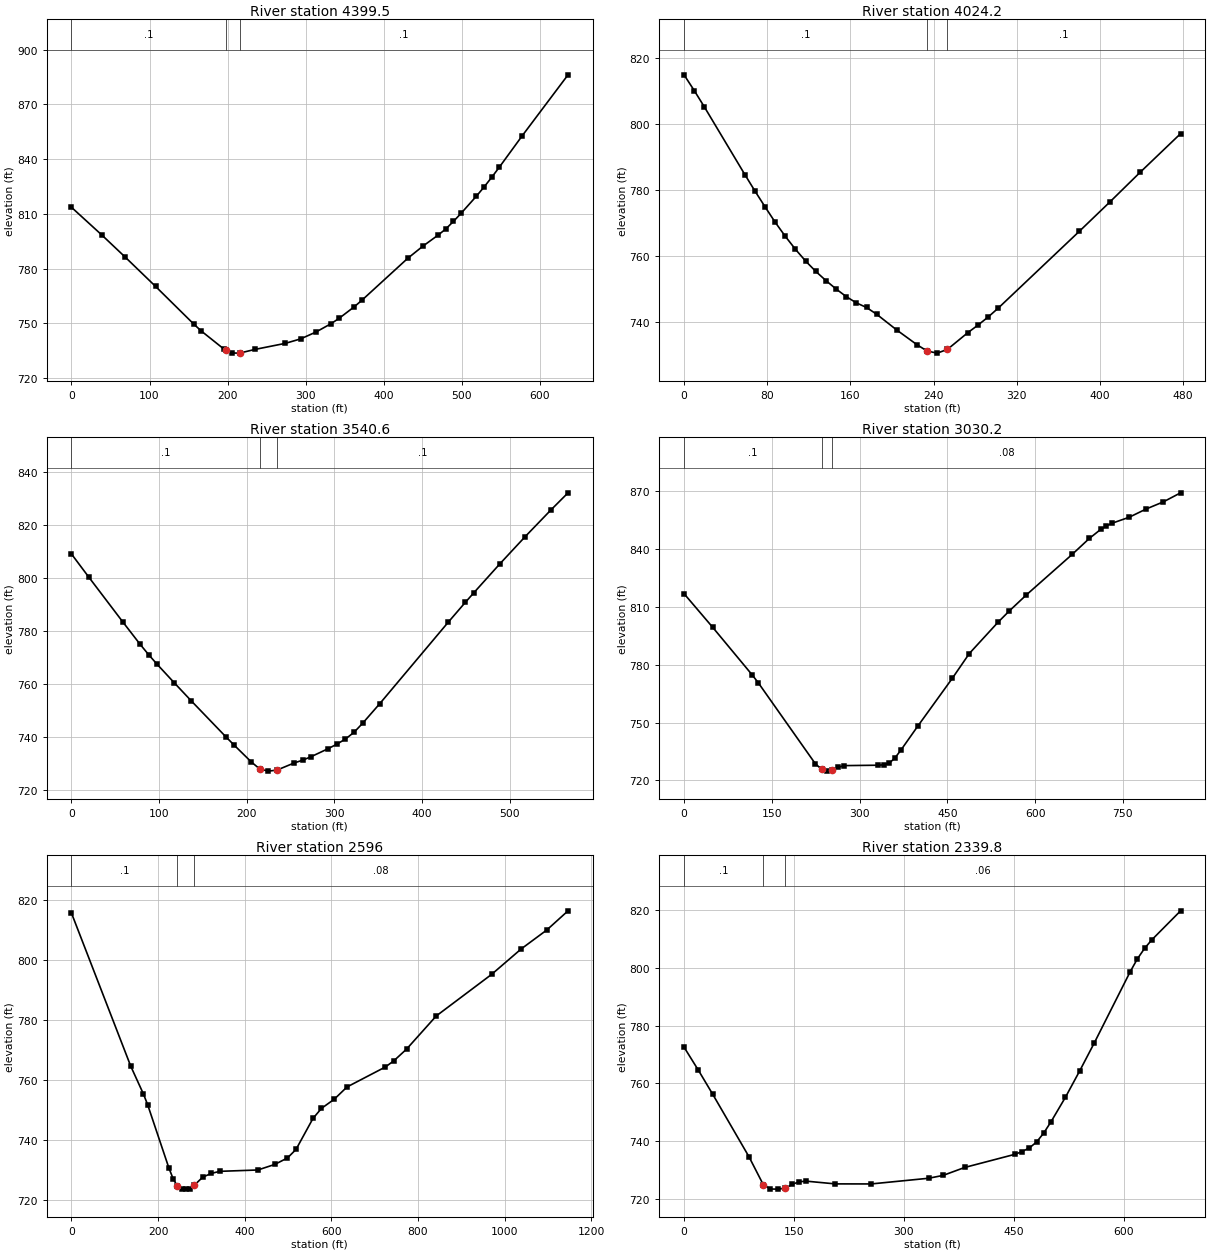
Type RM Length L Ch R = 1 ,4399.5  ,376.6,375.3,373.7
XS GIS Cut Line= 2
     1863885.064      611204.126     1863306.939      611469.751
#Sta/Elev= 30
       0  813.63    39.2  798.32    68.5  786.47   107.7  770.28   156.6  749.65
   166.4   745.8   195.8  735.76   198.2  735.28   205.6  733.78   215.3  733.71
   234.9  735.73   274.1  739.08   293.6  741.52   313.2  745.26   332.8  749.92
   342.6   752.7   362.2  759.08     372  762.66   430.7  785.64   450.2  792.33
   469.8  798.42   479.6  801.78   489.4  805.92   499.2  810.36   518.8  819.75
   528.6  824.75   538.4  830.08   548.1  835.59   577.5  852.85   636.2  886.25
#Mann= 3 , 0 , 0
       0      .1       0   198.2    .045       0   215.3      .1       0
Bank Sta=198.2,215.3
XS Rating Curve= 0 ,0
Exp/Cntr=0.3,0.1

Type RM Length L Ch R = 1 ,4024.2  ,486.3,483.7,481
XS GIS Cut Line= 2
     1863702.772      610876.001     1863280.897      611099.959
#Sta/Elev= 30
       0  814.82     9.8  810.07    19.5  805.14    58.5  784.64    68.2  779.67
      78  774.84    87.7  770.21    97.5  765.92   107.2  762.02     117  758.46
   126.7  755.36   136.5  752.57   146.2  750.05     156  747.73   165.7  745.84
   175.5  744.44   185.2  742.41   204.7   737.6   224.2  733.14   233.9  731.25
   243.6  730.63   253.4  731.78   272.9  736.81   282.7   739.1   292.4  741.53
   302.2  744.24   380.2  767.48   409.4   776.3   438.6   785.3   477.6  797.03
#Mann= 3 , 0 , 0
       0      .1       0   233.9    .045       0   253.4      .1       0
Bank Sta=233.9,253.4
XS Rating Curve= 0 ,0
Exp/Cntr=0.3,0.1

Type RM Length L Ch R = 1 ,3540.6  ,505.4,510.4,514.5
XS GIS Cut Line= 2
     1863418.918      610454.126     1862955.376      610779.647
#Sta/Elev= 30
       0  809.06    19.5  800.44    58.6   783.4    78.1  775.06    87.9  771.11
    97.7  767.44   117.2  760.47   136.7  753.62   175.8  740.18   185.6  736.92
   205.1   730.6   214.8  727.92   224.6  727.13   234.4  727.52   253.9   730.2
   263.7  731.26   273.4  732.59     293  735.64   302.7  737.31   312.5  739.24
   322.3  741.79     332  745.15   351.6  752.57   429.7  783.31   449.2   790.8
     459  794.46   488.3  805.23   517.6  815.65   546.9   825.7   566.4  832.15
#Mann= 3 , 0 , 0
       0      .1       0   214.8    .045       0   234.4      .1       0
Bank Sta=214.8,234.4
XS Rating Curve= 0 ,0
Exp/Cntr=0.3,0.1

Type RM Length L Ch R = 1 ,3030.2  ,436.4,434.2,432
XS GIS Cut Line= 3
     1863236.626      610045.272      1862788.71       610237.98
     1862718.397      610592.147
#Sta/Elev= 30
       0  816.91    48.8  799.51     117  774.55   126.8  770.69   224.3  728.67
   235.2  725.71   243.8  724.79   253.6  725.29   263.3  726.72   273.1  727.65
   331.6  727.86   341.3  728.07   351.1  728.99   360.8  731.76   370.6  735.68
   399.8  748.27   458.4  772.92   487.6  785.85   536.4     802   555.9  807.94
   585.2   816.3   663.3  837.28   692.6  845.56   712.1  850.27   721.8  852.08
   731.6  853.49   760.9   856.6   790.1  860.91   819.4   864.6   848.7  869.27
#Mann= 3 , 0 , 0
       0      .1       0   235.2    .045       0   253.6     .08       0
Bank Sta=235.2,253.6
XS Rating Curve= 0 ,0
Exp/Cntr=0.3,0.1

Type RM Length L Ch R = 1 ,2596    ,241.6,256.2,270.2
XS GIS Cut Line= 3
     1863107.122      609604.536     1862704.561      609825.891
     1862213.189      610305.688
#Sta/Elev= 30
       0  815.51   136.8  764.48   166.2  755.16   175.9   751.6   224.8  730.56
   234.6  726.96   244.4  724.51   254.1  723.57   263.9   723.5   273.7   723.6
   283.5   724.8     303   727.5   322.6  728.73   342.1  729.43   430.1  729.88
   469.2  731.73   498.6   733.9   518.3  736.74   557.5  747.08   577.1  750.43
   606.6  753.48     636  757.56   724.3   764.2   743.9  766.25   773.4  770.17
     842  781.23   969.6  795.07  1038.2  803.59  1097.1  809.88  1146.2  816.28
#Mann= 3 , 0 , 0
       0      .1       0   244.4    .045       0   283.5     .08       0
Bank Sta=244.4,283.5
XS Rating Curve= 0 ,0
Exp/Cntr=0.3,0.1

Type RM Length L Ch R = 1 ,2339.8  ,50.7,50.5,50.5
XS GIS Cut Line= 2
     1862984.022      609495.792     1862312.147      609409.855
#Sta/Elev= 30
       0  772.55    19.6  764.56    39.3   756.2    88.4  734.78     108   725.1
   117.8  723.55   127.6  723.51   138.3  723.83   147.2  725.12   157.1  726.06
   166.9  726.26   206.2  725.32   255.2   725.3   333.8  727.27   353.4  728.25
   382.8  730.99   451.6  735.55   461.4   736.5   471.2  737.76     481   739.8
   490.8  742.93   500.6  746.76   520.3  755.24   539.9  764.42   559.6  773.98
   608.6  798.58   618.4  803.03   628.3  806.68   638.1  809.61   677.4  819.64
#Mann= 3 , 0 , 0
       0      .1       0     108    .045       0   138.3     .06       0
Bank Sta=108,138.3
XS Rating Curve= 0 ,0
Exp/Cntr=0.3,0.1

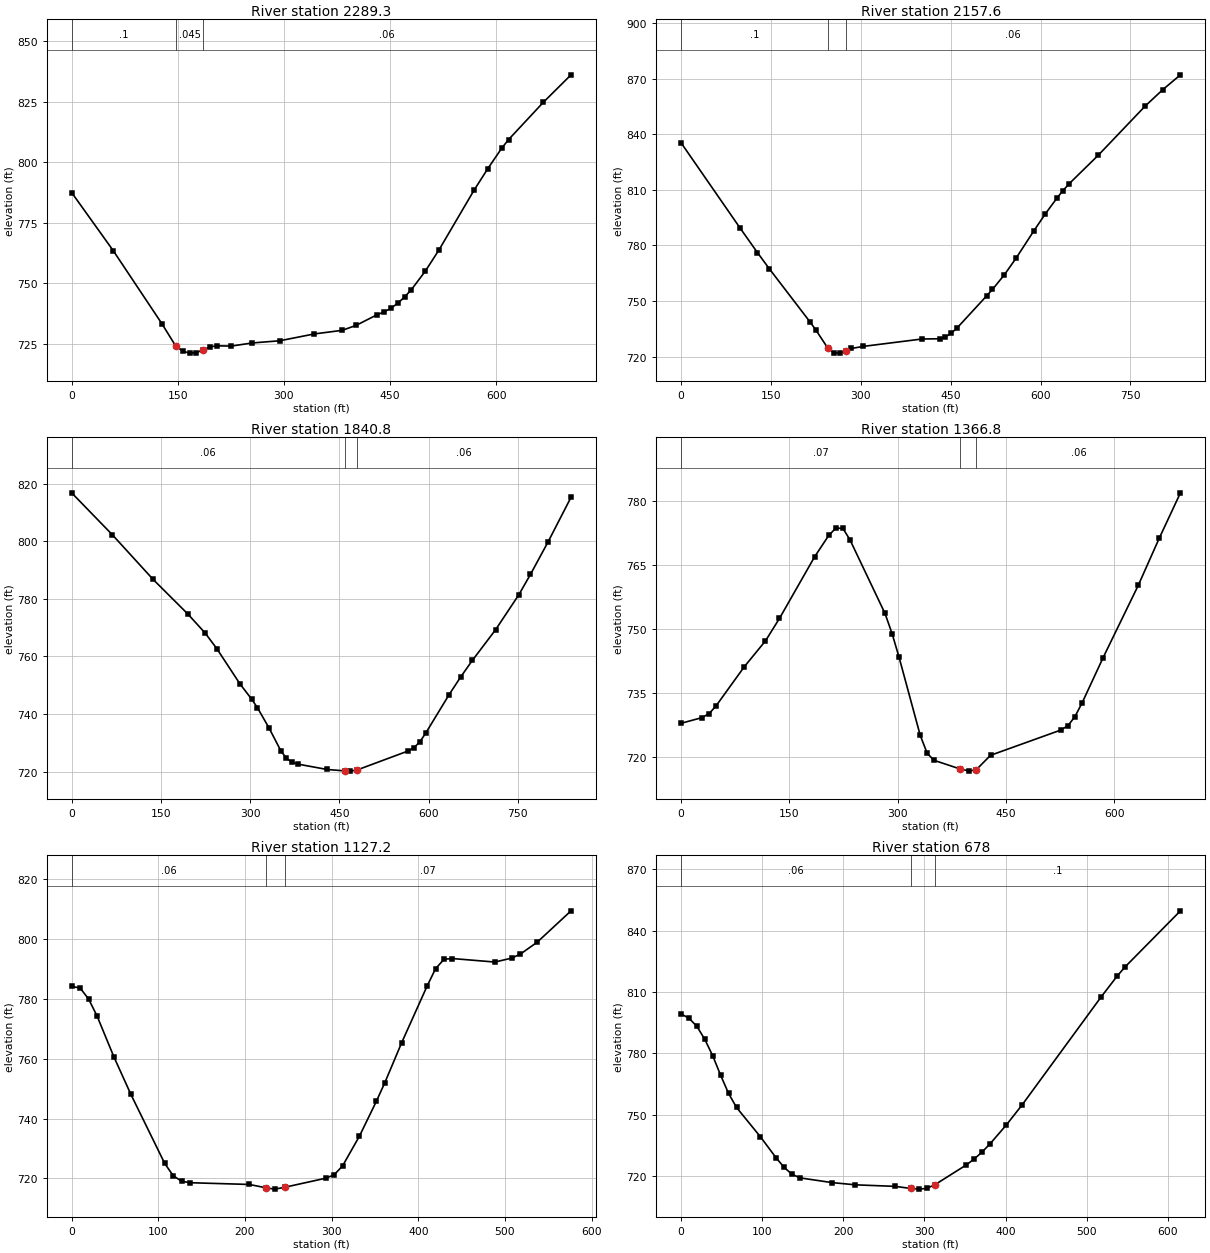
Type RM Length L Ch R = 1 ,2289.3  ,134.4,131.7,129.3
XS GIS Cut Line= 2
     1863015.272      609448.917     1862314.751       609362.98
#Sta/Elev= 30
       0  787.45    58.8  763.42   127.4  733.31     147  724.05   156.8  721.92
   166.6  721.07   176.4  721.27   186.2  722.48     196   723.7   205.8  724.09
   225.5  723.98   254.9  725.26   294.1  726.18   343.1  729.01   382.3  730.49
   401.9  732.52   431.3  736.88   441.1  738.06   450.9  739.56   460.7  741.64
   470.5  744.25   480.3  747.36   499.9  754.98   519.5  763.88   568.5  788.31
   588.1  797.29   607.8  805.76   617.6  809.36   666.6  824.73   705.8   836.1
#Mann= 3 , 0 , 0
       0      .1       0     147    .045       0   186.2     .06       0
Bank Sta=147,186.2
XS Rating Curve= 0 ,0
Exp/Cntr=0.3,0.1

Type RM Length L Ch R = 1 ,2157.6  ,317.9,316.8,314.8
XS GIS Cut Line= 2
     1863106.418       609300.48     1862273.085      609290.063
#Sta/Elev= 30
       0  835.42      98  789.64   127.5  776.15   147.1  767.52   215.7  738.54
   225.5  734.13   245.1  724.52   254.9  722.02   264.7   721.9   274.5  723.16
   284.3  724.41     304  725.53     402  729.52   431.4  729.65   441.2  730.63
     451  732.68   460.8  735.53   509.8  752.74   519.6  756.24   539.3  764.08
   558.9  773.03   588.3  787.66   607.9  797.05   627.5  805.63   637.3  809.58
   647.1  813.12   696.1  828.64   774.6  855.24     804   864.1   833.4  872.08
#Mann= 3 , 0 , 0
       0      .1       0   245.1    .045       0   274.5     .06       0
Bank Sta=245.1,274.5
XS Rating Curve= 0 ,0
Exp/Cntr=0.3,0.1

Type RM Length L Ch R = 1 ,1840.8  ,487.1,474,460.5
XS GIS Cut Line= 2
     1863292.036      608958.649      1862453.91      609008.833
#Sta/Elev= 30
       0  816.89    68.3  802.34   136.7  786.85   195.3  774.78   224.6  768.12
   244.1  762.71   283.1  750.44   302.7  745.15   312.4  742.18     332   735.1
   351.5   727.3   361.2  724.57     371  723.18   380.8  722.57   429.6  720.72
   458.9  720.24   468.6  720.15   479.7  720.54   566.3   727.2     576  728.34
   585.8  730.44   595.6  733.47   634.6  746.73   654.1  752.89   673.6  758.61
   712.7  769.29   751.8  781.45   771.3  788.51   800.6  799.68   839.6  815.35
#Mann= 3 , 0 , 0
       0     .06       0   458.9    .045       0   479.7     .06       0
Bank Sta=458.9,479.7
XS Rating Curve= 0 ,0
Exp/Cntr=0.3,0.1

Type RM Length L Ch R = 1 ,1366.8  ,233.5,239.6,245.7
XS GIS Cut Line= 2
     1862976.744      608315.468     1862423.528      608731.055
#Sta/Elev= 30
       0   727.9    29.2  729.23      39  730.18    48.7  732.01    87.7  741.14
     117  747.18   136.4  752.44   185.2  766.88   204.6  771.82   214.4  773.55
   224.2  773.49   233.9  770.86   282.6  753.58   292.4  748.87   302.1  743.32
   331.3  725.12   341.1  720.84   350.8  719.22   386.2  717.24   399.6  716.71
   409.3  717.09   428.8  720.41   526.2  726.32     536  727.33   545.7  729.46
   555.5  732.62   584.7  743.23   633.4  760.14   662.7  771.25   691.9   781.8
#Mann= 3 , 0 , 0
       0     .07       0   386.2    .045       0   409.3     .06       0
Bank Sta=386.2,409.3
XS Rating Curve= 0 ,0
Exp/Cntr=0.3,0.1

Type RM Length L Ch R = 1 ,1127.2  ,435.9,449.2,462.1
XS GIS Cut Line= 2
     1862725.177      608284.007     1862191.323      608501.021
#Sta/Elev= 30
       0  784.12     9.8  783.56    19.5  779.94    29.3  774.25    48.8  760.56
    68.4  748.04   107.4  725.01   117.2  720.91     127  719.05   136.7  718.57
   205.1  717.99   224.6  716.85   234.4  716.43   245.9  717.05     293  720.06
   302.8  721.18   312.6  724.16   332.1  734.11   351.6  745.72   361.4  751.95
   380.9  765.35   410.2  784.22     420  790.04   429.8  793.18   439.5  793.41
   488.4  792.24   507.9  793.56   517.7  794.87   537.2  798.85   576.3  809.34
#Mann= 3 , 0 , 0
       0     .06       0   224.6    .045       0   245.9     .07       0
Bank Sta=224.6,245.9
XS Rating Curve= 0 ,0
Exp/Cntr=0.3,0.1

Type RM Length L Ch R = 1 ,678     ,241.8,252.2,262.7
XS GIS Cut Line= 2
     1862670.924      608058.312     1862069.795      607925.934
#Sta/Elev= 30
       0  799.26     9.8  797.14    19.5  793.17    29.3  786.79    39.1  778.71
    48.8  769.23    58.6  760.32    68.4  753.46    97.7  739.18   117.2  728.81
     127  724.14   136.8  720.76   146.6  719.01   185.6  716.72     215   715.6
   263.8  714.85   283.3  713.83   293.1   713.5   302.9  713.87   313.2  715.74
   351.7  725.38   361.5   728.3   371.3  731.76     381  735.75   400.6  744.76
   420.1  754.58   517.8   807.6   537.4  817.72   547.1   822.2   615.5  849.71
#Mann= 3 , 0 , 0
       0     .06       0   283.3    .045       0   313.2      .1       0
Bank Sta=283.3,313.2
XS Rating Curve= 0 ,0
Exp/Cntr=0.3,0.1

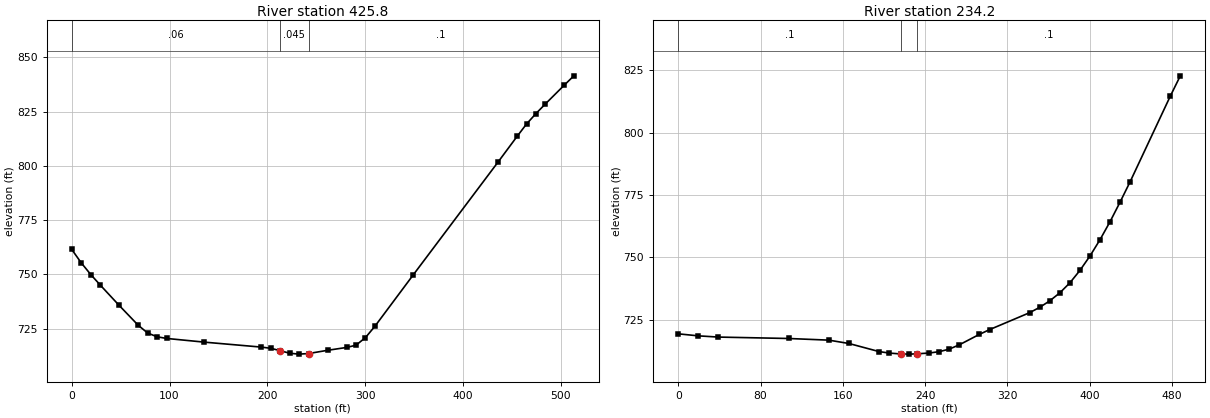
Type RM Length L Ch R = 1 ,425.8   ,188.8,191.6,194.2
XS GIS Cut Line= 2
     1862675.264      607910.743     1862269.448      607596.073
#Sta/Elev= 29
       0  761.53     9.7  755.36    19.4  749.99    29.1  745.15    48.4  735.79
    67.8  726.69    77.5  723.07    87.2  721.31    96.9  720.55   135.6  718.84
   193.8  716.56   203.5  716.01   213.2  714.91   222.8  713.73   232.5  713.32
   242.2  713.59   261.6  715.08     281  716.39   290.7  717.43   300.4  720.95
     310  726.13   348.8  749.56     436  801.81   455.4  813.58   465.1  819.32
   474.8  824.15   484.4  828.57   503.8  837.26   513.5  841.51
#Mann= 3 , 0 , 0
       0     .06       0   213.2    .045       0   242.2      .1       0
Bank Sta=213.2,242.2
XS Rating Curve= 0 ,0
Exp/Cntr=0.3,0.1

Type RM Length L Ch R = 1 ,234.2   ,213.2,234.2,255.3
XS GIS Cut Line= 2
      1862764.24      607771.854     1862414.847      607431.142
#Sta/Elev= 30
       0  719.42    19.5  718.61      39  718.12   107.4  717.55   146.4  716.89
   165.9  715.55   195.2  712.31     205  711.72   216.8  711.34   224.5  711.29
   231.8   711.4     244  711.74   253.8  712.28   263.5  713.31   273.3  715.04
   292.8  719.22   302.6   721.1   341.6   727.9   351.4  730.05   361.1  732.63
   370.9  735.84   380.6  739.81   390.4   744.8   400.2   750.6   409.9  757.09
   419.7  764.34   429.4  772.14   439.2  780.32   478.3  814.65     488  822.76
#Mann= 3 , 0 , 0
       0      .1       0   216.8    .045       0   231.8      .1       0
Bank Sta=216.8,231.8
XS Rating Curve= 0 ,0
Exp/Cntr=0.3,0.1

Chan Stop Cuts=-1
Use User Specified Reach Order=0
Composite Channel Slope=5